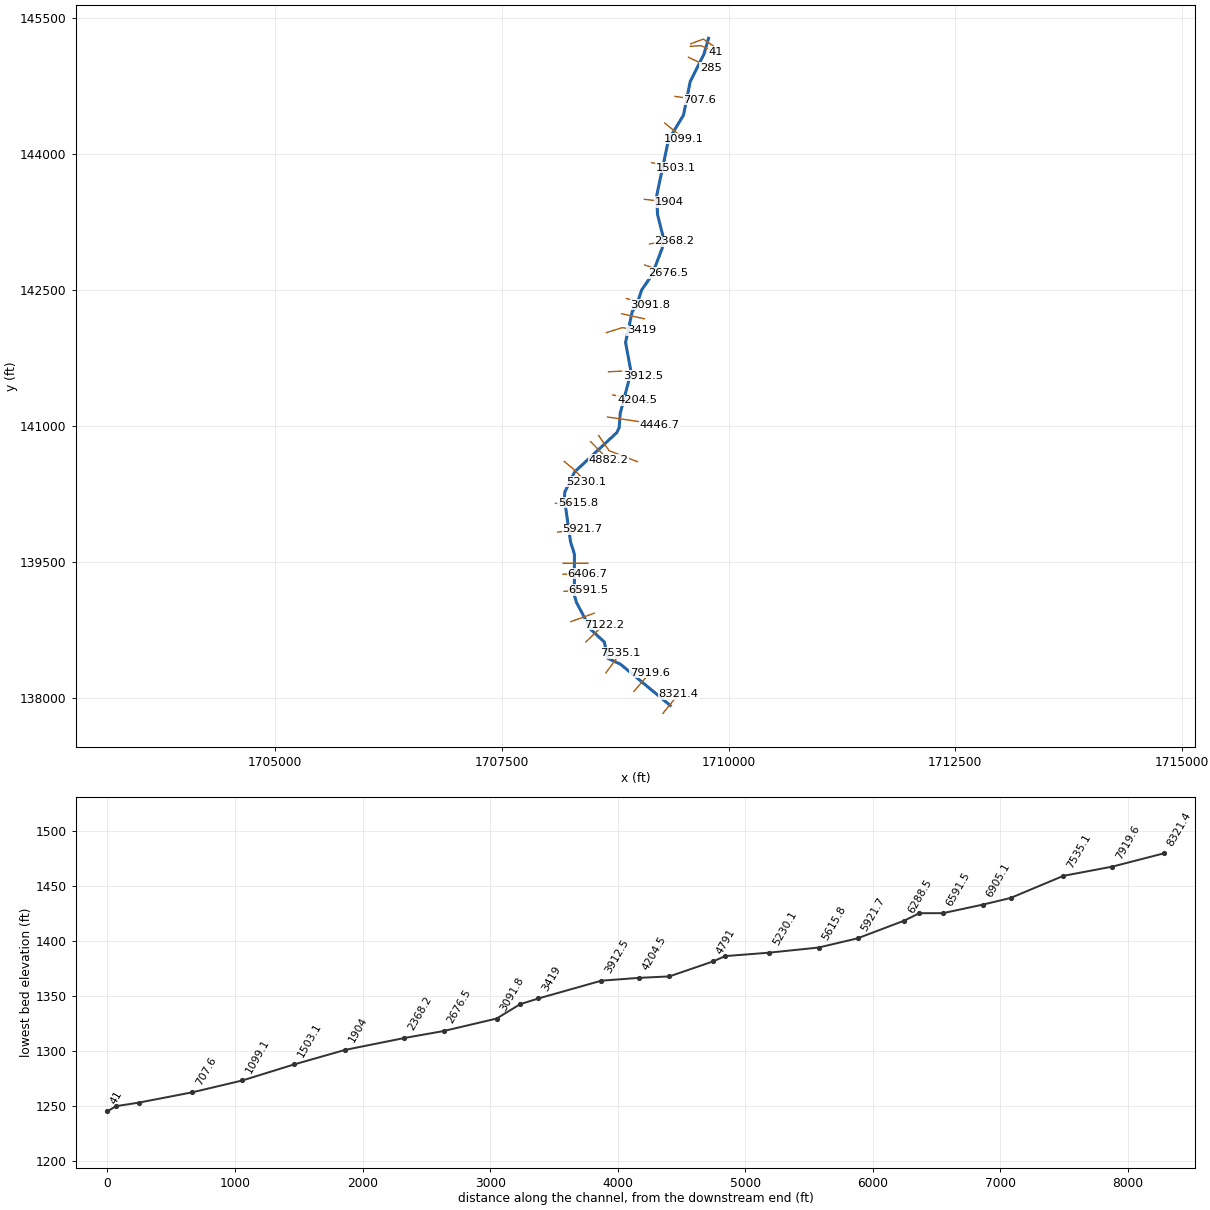
--- Middle Fork Panther Creek.prj (project) ---

Proj Title=Middle Fork Panther Creek
Current Plan=p01
Default Exp/Contr=0,0
English Units
Geom File=g01
Flow File=f01
Plan File=p01
BEGIN DESCRIPTION:
END DESCRIPTION:
DSS Export Rating Curves= 0
DSS Export Rating Curve Sorted= 0
DSS Export Volume Flow Curves= 0
DXF OffsetX= 0
DXF OffsetY= 0
DXF ScaleX= 0
DXF ScaleY= 0

--- Middle Fork Panther Creek.p01 (plan) ---

Plan Title=Floodplain
Program Version=4.00
Geom File=g01
Flow File=f01
K Sum by GR=0
Std Step Tol=0.01
Critical Tol=0.01
Num of Std Step Trials=20
Max Error Tol=0.3
Flow Tol Ratio=0.001
Split Flow NTrial=30
Split Flow Tol=0.02
Split Flow Ratio=0.02
Log Output Level=0
Friction Slope Method=1
Unsteady Friction Slope Method=2
Unsteady Bridges Friction Slope Method=1
Global Log Level=0
CheckData=False
Run HTab=0
Run UNet=0
Run PostProcess=0
UNET Theta=0
UNET Theta Warmup=0
UNET ZTol=0
UNET ZSATol=0
UNET MxIter=0
UNET MaxInSteps=0
UNET DtIC=0
UNET DtMin=0
UNET MaxCRTS=0
UNET WFStab=0
UNET SFStab=0
UNET WFX=0
UNET SFX=0
UNET DSS MLevel=0
UNET DZMax Abort=0
UNET Convert EG Bridges=0
UNET Use Existing IB Tables=0
UNET Froude Limit=0
UNET Froude Power=0
Write IC File=0
Echo Input=False
Echo Output=False
Write Detailed=0

--- Middle Fork Panther Creek.f01 (steady flow) ---

Flow Title=NFF Regression Equation
Program Version=4.00
Number of Profiles=1
Profile Names=P100yr
River Rch & RM=Middle Fork P...,Main      ,8321.4
574.9559
River Rch & RM=Middle Fork P...,Main      ,6905.1
610.6561
River Rch & RM=Middle Fork P...,Main      ,6591.5
675.3505
River Rch & RM=Middle Fork P...,Main      ,5230.1
725.2256
River Rch & RM=Middle Fork P...,Main      ,4204.5
802.5058
River Rch & RM=Middle Fork P...,Main      ,2676.5
840.7990
River Rch & RM=Middle Fork P...,Main      ,2368.2
929.0681
River Rch & RM=Middle Fork P...,Main      ,285
960.1525
Boundary for River Rch & Prof#=Middle Fork P...,Main      ,1
Up Type=0
Dn Type=3
Dn Slope=0.037452

--- Middle Fork Panther Creek.g01 (geometry) ---

Geom Title=Geometry
Program Version=4.00

River Reach=Middle Fork P...,Main
Reach XY= 30
     1709357.569      137922.625     1708809.877      138376.479
     1708668.828      138442.215     1708631.233      138621.109
     1708480.819      138761.592     1708327.043       139052.11
     1708300.873      139135.358      1708301.49      139591.692
      1708259.15      139724.506     1708190.881      140200.003
     1708195.564      140275.096     1708303.539       140496.87
     1708769.053      140930.457     1708794.609      140984.613
     1708806.207      141142.028     1708925.833      141598.718
     1708865.374      141923.651     1708939.849      142269.131
     1708983.102      142317.255     1709041.787      142501.339
     1709156.707       142667.51     1709269.177      142962.239
     1709274.623      143107.722     1709218.608      143330.224
     1709206.533      143534.328     1709338.431      144157.039
     1709503.822      144429.209      1709578.13      144801.309
     1709728.185      145098.573     1709779.884      145276.304

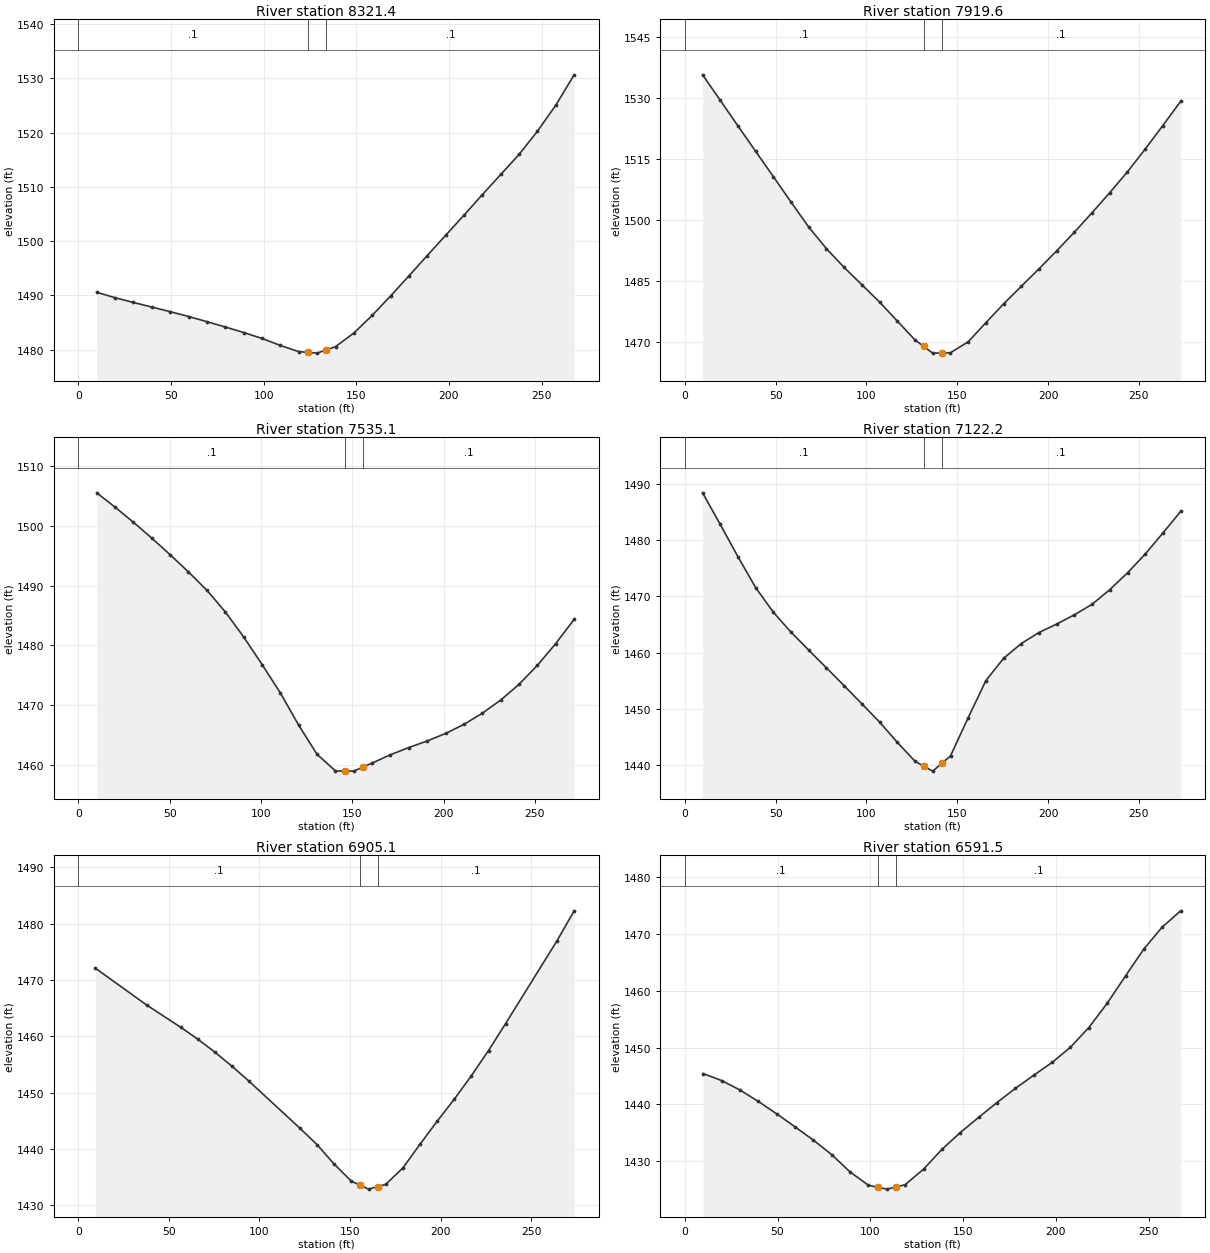
Type RM Length L Ch R = 1 ,8321.4  ,402.9,401.7,400.6
XS GIS Cut Line= 2
     1709277.236      137835.084     1709445.361      138043.313
#Sta/Elev= 29
     9.9 1490.55    19.8 1489.56    29.7 1488.68    39.6 1487.84    49.6 1486.98
    59.5 1486.09    69.4 1485.14    79.3 1484.16    89.2 1483.14    99.1 1482.05
     109 1480.76   118.9 1479.61   123.9 1479.48   128.9 1479.34   133.9 1479.95
   138.8 1480.54   148.7 1483.04   158.6  1486.3   168.5 1489.87   178.4 1493.57
   188.3 1497.32   198.2 1501.04   208.2 1504.79   218.1 1508.57     228 1512.28
   237.9 1515.98   247.8 1520.25   257.7 1525.05   267.6 1530.64
#Mann= 3 , 0 , 0
       0      .1       0   123.9    .045       0   133.9      .1       0
Bank Sta=123.9,133.9
XS Rating Curve= 0 ,0
Exp/Cntr=0.3,0.1

Type RM Length L Ch R = 1 ,7919.6  ,383,384.5,386
XS GIS Cut Line= 3
     1708956.375      138076.632     1709045.406      138180.101
     1709134.436       138283.57
#Sta/Elev= 30
     9.8 1535.76    19.5 1529.51    29.2 1523.24      39 1516.96    48.8 1510.71
    58.5 1504.48    68.2 1498.36      78 1493.03    87.7 1488.43    97.5 1484.15
   107.3 1479.88     117 1475.24   126.7 1470.62   131.5 1469.02   136.5 1467.35
   141.5 1467.39   146.2 1467.43     156 1470.12   165.7 1474.79   175.5 1479.44
   185.2 1483.74     195 1488.06   204.7 1492.47   214.5 1497.07   224.2 1501.85
     234  1506.8   243.7 1511.91   253.5 1517.51   263.2 1523.29     273 1529.23
#Mann= 3 , 0 , 0
       0      .1       0   131.5    .045       0   141.5      .1       0
Bank Sta=131.5,141.5
XS Rating Curve= 0 ,0
Exp/Cntr=0.3,0.1

Type RM Length L Ch R = 1 ,7535.1  ,416,412.9,409.5
XS GIS Cut Line= 2
     1708647.921      138280.848     1708808.335      138499.874
#Sta/Elev= 29
    10.1 1505.51    20.1 1503.12    30.2 1500.58    40.2 1497.94    50.3 1495.15
    60.3 1492.29    70.4 1489.21    80.4 1485.63    90.5 1481.43   100.6  1476.8
   110.6 1472.06   120.7 1466.63   130.7 1461.79   140.8    1459   145.8 1458.98
   150.8 1458.97   155.8 1459.64   160.9 1460.32   170.9 1461.71     181 1462.92
     191 1464.01   201.1 1465.27   211.2  1466.8   221.2 1468.65   231.3 1470.86
   241.3 1473.48   251.4 1476.67   261.4  1480.3   271.5 1484.36
#Mann= 3 , 0 , 0
       0      .1       0   145.8    .045       0   155.8      .1       0
Bank Sta=145.8,155.8
XS Rating Curve= 0 ,0
Exp/Cntr=0.3,0.1

Type RM Length L Ch R = 1 ,7122.2  ,225.6,217.2,209
XS GIS Cut Line= 3
     1708428.114      138622.737     1708525.938      138717.963
     1708625.182      138811.675
#Sta/Elev= 30
     9.8 1488.42    19.5 1482.81    29.3 1477.04      39 1471.56    48.8 1467.16
    58.5 1463.63    68.3 1460.42      78 1457.28    87.8 1454.09    97.5 1450.88
   107.3 1447.62     117 1444.04   126.8 1440.65   131.5 1439.81   136.5 1438.91
   141.5  1440.3   146.3 1441.63     156 1448.39   165.8 1455.03   175.5 1458.97
   185.3 1461.61     195 1463.57   204.8 1465.08   214.5 1466.72   224.3  1468.6
     234  1471.2   243.8  1474.2   253.5 1477.53   263.3 1481.29     273  1485.1
#Mann= 3 , 0 , 0
       0      .1       0   131.5    .045       0   141.5      .1       0
Bank Sta=131.5,141.5
XS Rating Curve= 0 ,0
Exp/Cntr=0.3,0.1

Type RM Length L Ch R = 1 ,6905.1  ,319.6,313.6,307.6
XS GIS Cut Line= 3
     1708261.239      138846.484     1708385.707       138890.11
     1708518.701      138939.496
#Sta/Elev= 24
     9.4 1472.09    37.7 1465.56    56.5 1461.61    65.9 1459.51    75.4 1457.19
    84.8  1454.7    94.2 1452.05   122.5 1443.65   131.9 1440.75   141.3 1437.32
   150.8 1434.28   155.3 1433.62   160.3 1432.88   165.3 1433.33   169.7 1433.72
   179.2 1436.63   188.6 1440.81   198.1 1444.91   207.6 1448.84     217 1452.99
   226.5 1457.47   235.9 1462.24   264.3 1476.94   273.8 1482.27
#Mann= 3 , 0 , 0
       0      .1       0   155.3    .045       0   165.3      .1       0
Bank Sta=155.3,165.3
XS Rating Curve= 0 ,0
Exp/Cntr=0.3,0.1

Type RM Length L Ch R = 1 ,6591.5  ,185.4,184.7,184
XS GIS Cut Line= 2
     1708186.733      139180.089     1708453.574      139195.513
#Sta/Elev= 29
     9.9 1445.44    19.8 1444.22    29.7 1442.56    39.6 1440.54    49.5 1438.36
    59.4 1436.06    69.3 1433.72    79.2 1431.16    89.1 1428.11      99 1425.76
   103.9 1425.42   108.9 1425.08   113.9 1425.47   118.8 1425.86   128.7  1428.6
   138.6 1432.08   148.5 1435.04   158.4 1437.72   168.3 1440.33   178.2 1442.83
   188.1 1445.14     198  1447.4   207.9 1450.08   217.8 1453.55   227.7 1457.82
   237.6 1462.65   247.5  1467.4   257.4 1471.26   267.3 1474.12
#Mann= 3 , 0 , 0
       0      .1       0   103.9    .045       0   113.9      .1       0
Bank Sta=103.9,113.9
XS Rating Curve= 0 ,0
Exp/Cntr=0.3,0.1

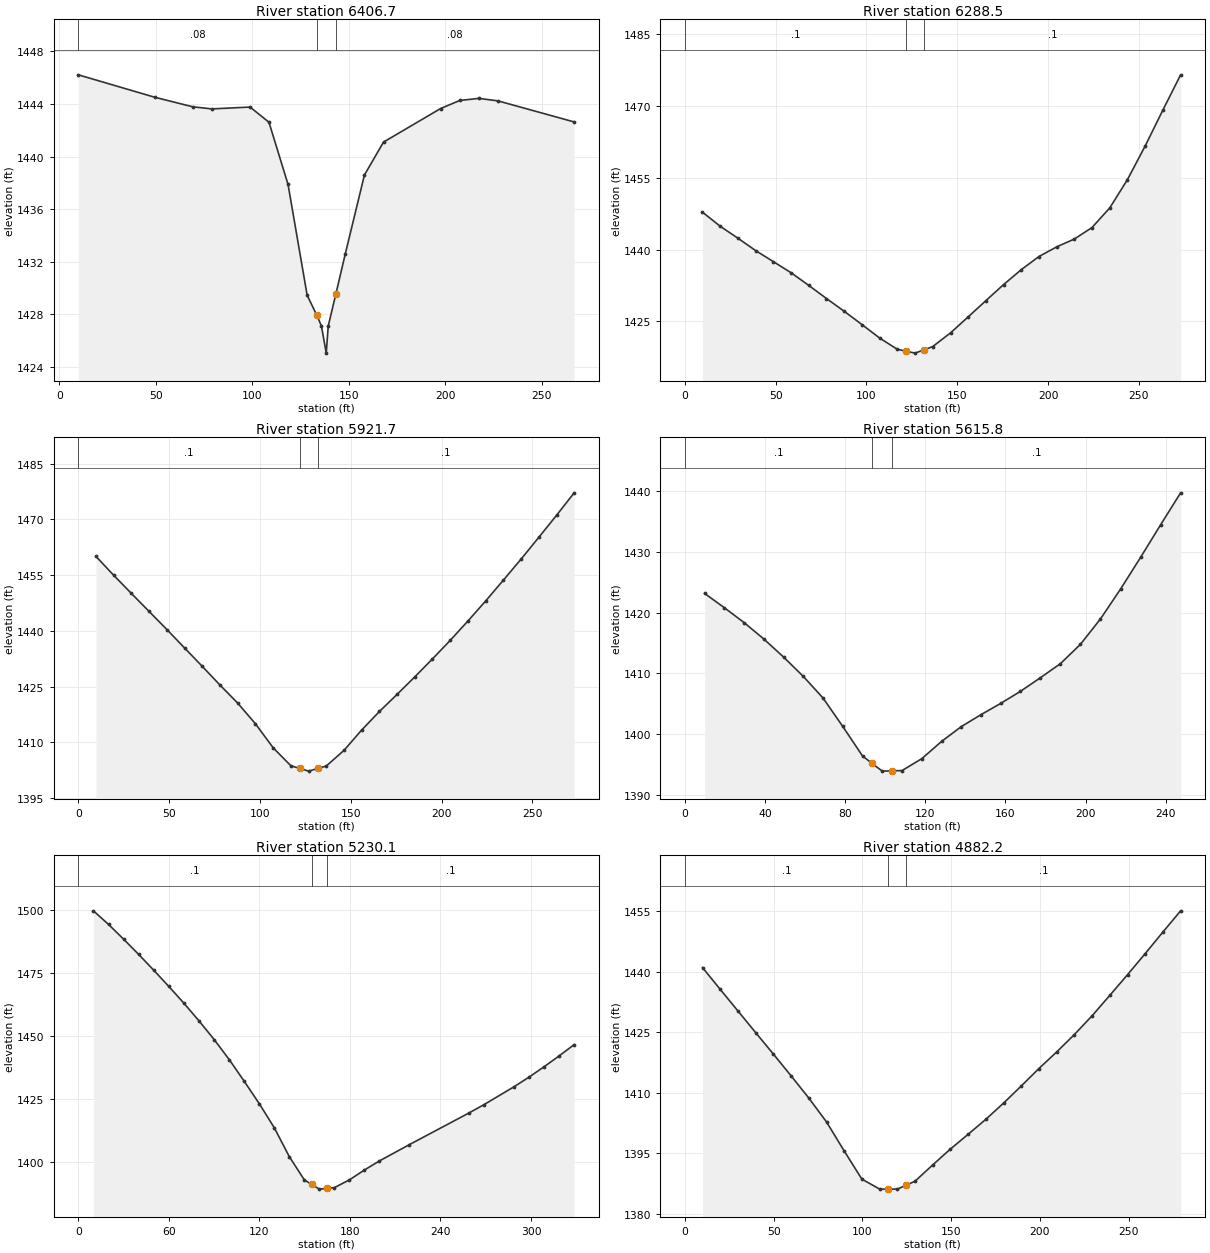
Type RM Length L Ch R = 1 ,6406.7  ,118.7,118.2,117.8
XS GIS Cut Line= 2
     1708175.936      139368.266     1708442.777      139374.436
#Sta/Elev= 21
     9.9 1446.21    49.4 1444.51    69.2 1443.78    79.1 1443.62    98.9 1443.76
   108.7 1442.61   118.6 1437.88   128.5 1429.46   133.4 1427.97  135.91 1427.12
   138.4 1425.06  139.43 1427.12   143.4 1429.56   148.3 1432.62   158.2  1438.6
   168.1  1441.1   197.7 1443.65   207.6 1444.26   217.5 1444.42   227.4 1444.23
   266.9 1442.63
#Mann= 3 , 0 , 0
     9.9     .08       0   133.4    .045       0   143.4     .08       0
Bank Sta=133.4,143.4
XS Rating Curve= 0 ,0
Exp/Cntr=0.3,0.1

Type RM Length L Ch R = 1 ,6288.5  ,364.5,366.8,369.1
XS GIS Cut Line= 3
     1708176.602       139489.32     1708313.102      139489.568
     1708449.601      139489.816
#Sta/Elev= 30
     9.7 1447.82    19.5 1444.86    29.2 1442.38      39 1439.78    48.7 1437.48
    58.5 1435.15    68.3 1432.49      78 1429.76    87.8 1427.08    97.5 1424.32
   107.3 1421.49     117 1419.14   121.8 1418.75   126.8 1418.34   131.8 1419.05
   136.5 1419.71   146.3 1422.57     156 1425.91   165.8 1429.32   175.5 1432.66
   185.3  1435.8     195 1438.54   204.8 1440.56   214.5  1442.2   224.2 1444.59
     234 1448.71   243.7  1454.6   253.5 1461.66   263.2 1469.13     273 1476.52
#Mann= 3 , 0 , 0
       0      .1       0   121.8    .045       0   131.8      .1       0
Bank Sta=121.8,131.8
XS Rating Curve= 0 ,0
Exp/Cntr=0.3,0.1

Type RM Length L Ch R = 1 ,5921.7  ,308.2,305.9,303.5
XS GIS Cut Line= 3
     1708116.109      139833.553     1708251.675      139849.502
     1708387.239      139865.451
#Sta/Elev= 30
     9.7 1460.01    19.5 1454.91    29.2 1450.05      39 1445.18    48.8 1440.31
    58.5 1435.36    68.3 1430.39      78 1425.39    87.8 1420.51    97.5 1414.98
   107.3  1408.5     117 1403.69   121.8 1402.97   126.8 1402.23   131.8 1402.94
   136.5  1403.6   146.3 1407.83     156 1413.29   165.8 1418.29   175.5 1422.88
   185.2 1427.57     195 1432.43   204.8 1437.43   214.5 1442.62   224.3 1448.03
     234  1453.6   243.8 1459.29   253.5 1465.11   263.3 1471.06     273 1477.11
#Mann= 3 , 0 , 0
       0      .1       0   121.8    .045       0   131.8      .1       0
Bank Sta=121.8,131.8
XS Rating Curve= 0 ,0
Exp/Cntr=0.3,0.1

Type RM Length L Ch R = 1 ,5615.8  ,401.5,385.7,370
XS GIS Cut Line= 3
     1708092.644      140150.281     1708270.024      140150.281
     1708339.434      140159.536
#Sta/Elev= 27
     9.9 1423.16    19.7 1420.82    29.6 1418.35    39.4 1415.66    49.3 1412.67
    59.1  1409.5      69 1405.91    78.8 1401.24    88.7 1396.36    93.5 1395.14
    98.5 1393.87   103.5 1393.92   108.4 1393.96   118.3 1395.94   128.1 1398.76
     138 1401.22   147.8 1403.18   157.7 1405.05   167.5 1407.03   177.4 1409.26
   187.4 1411.58   197.4 1414.77   207.4 1418.96   217.4 1423.87   227.4  1429.1
   237.4 1434.47   247.4 1439.75
#Mann= 3 , 0 , 0
       0      .1       0    93.5    .045       0   103.5      .1       0
Bank Sta=93.5,103.5
XS Rating Curve= 0 ,0
Exp/Cntr=0.3,0.1

Type RM Length L Ch R = 1 ,5230.1  ,348.1,347.9,347.7
XS GIS Cut Line= 3
     1708188.865      140612.759     1708281.221      140536.172
     1708429.128      140389.031
#Sta/Elev= 30
      10 1499.86      20 1494.46      30  1488.6      40 1482.52      50 1476.24
      60 1469.78      70 1463.12      80 1456.09      90  1448.7     100 1440.73
     110 1432.05     120 1423.12   129.9 1413.59   139.8 1402.16   149.8 1392.89
   154.7 1391.08   159.7 1389.23   164.7 1389.53   169.7 1389.83   179.6 1392.89
   189.5 1396.79   199.5 1400.43   219.3 1406.89   259.1 1419.57     269 1422.87
   288.9 1429.98   298.8  1433.8   308.7 1437.89   318.7 1442.21   328.6 1446.68
#Mann= 3 , 0 , 0
       0      .1       0   154.7    .045       0   164.7      .1       0
Bank Sta=154.7,164.7
XS Rating Curve= 0 ,0
Exp/Cntr=0.3,0.1

Type RM Length L Ch R = 1 ,4882.2  ,94.6,91.1,87.7
XS GIS Cut Line= 2
     1708479.796      140830.496     1708675.685      140631.522
#Sta/Elev= 30
      10 1440.99    19.9 1435.63    29.9 1430.26    39.9 1424.88    49.9 1419.55
    59.8 1414.19    69.8 1408.68    79.8 1402.74    89.7 1395.58    99.7 1388.57
   109.7 1386.09   114.7 1386.09   119.7 1386.08   124.7 1387.07   129.6 1388.03
   139.6 1392.08   149.6 1396.03   159.6 1399.69   169.5 1403.38   179.5 1407.41
   189.5 1411.66   199.4 1415.98   209.4 1420.08   219.4 1424.41   229.4 1429.08
   239.3  1434.1   249.3 1439.24   259.3 1444.49   269.2  1449.8   279.2 1455.07
#Mann= 3 , 0 , 0
       0      .1       0   114.7    .045       0   124.7      .1       0
Bank Sta=114.7,124.7
XS Rating Curve= 0 ,0
Exp/Cntr=0.3,0.1

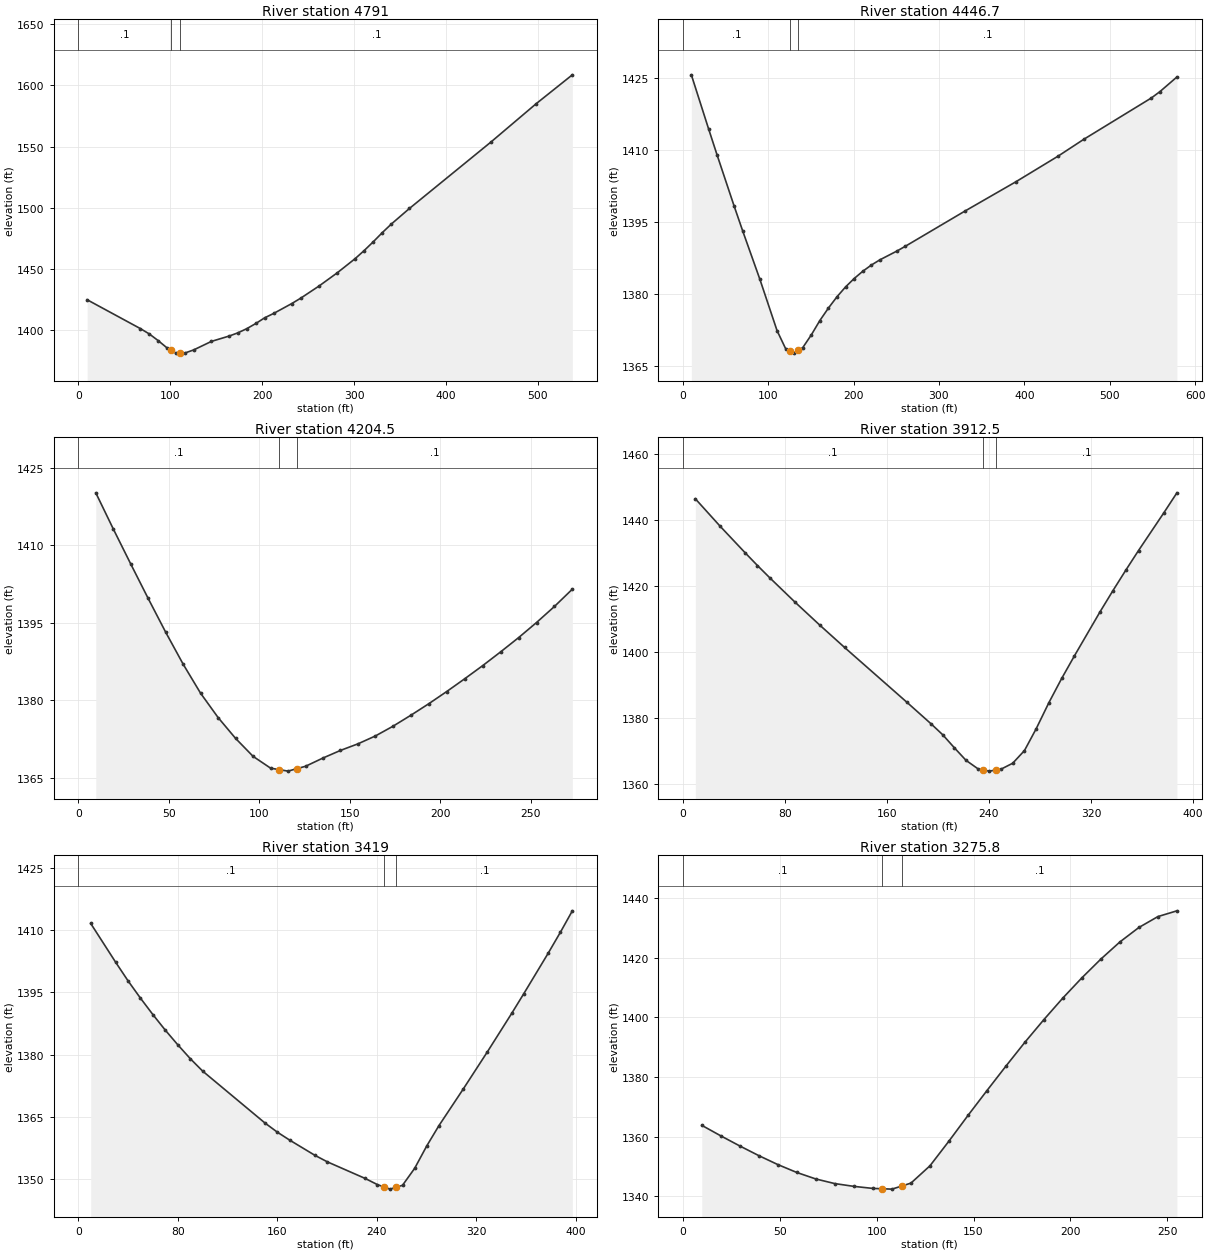
Type RM Length L Ch R = 1 ,4791    ,327.9,344.4,360.9
XS GIS Cut Line= 3
     1708567.715      140898.363     1708683.157      140731.613
      1708994.97      140609.928
#Sta/Elev= 30
     9.7 1424.94    67.6 1401.38    77.3 1397.02    86.9 1391.61    96.6 1385.61
   101.2 1383.57   106.2 1381.35   111.2 1381.38   115.9 1381.41   125.5 1383.95
   144.9 1390.94   164.2 1395.31   173.8 1397.96   183.5 1401.39   193.2 1405.57
   202.8  1410.2   212.7 1413.82   232.3 1421.85   242.2 1426.33   261.9 1436.14
   281.6 1446.86   301.3 1458.58   311.1 1465.17   320.9 1472.26   330.8  1479.8
   340.6 1486.79   360.3 1499.53   448.9 1553.75   498.1 1585.05   537.5 1608.67
#Mann= 3 , 0 , 0
       0      .1       0   101.2    .045       0   111.2      .1       0
Bank Sta=101.2,111.2
XS Rating Curve= 0 ,0
Exp/Cntr=0.3,0.1

Type RM Length L Ch R = 1 ,4446.7  ,243.4,242.1,240.9
XS GIS Cut Line= 3
     1708666.431      141101.965     1708914.763      141066.489
     1709238.675      141015.588
#Sta/Elev= 30
      10 1425.58    30.1 1414.39    40.1 1408.93    60.2 1398.23    70.2 1393.07
    90.3 1383.02   110.4 1372.35   120.4 1368.62   125.4 1368.15   130.4 1367.68
   135.4 1368.25   140.5 1368.83   150.5 1371.47   160.5 1374.46   170.6 1377.07
   180.6 1379.41   190.6 1381.45   200.7  1383.2   210.7  1384.7   220.8    1386
   230.8 1387.09   250.9 1388.93   260.8 1389.93   330.3 1397.22     390 1403.32
   439.6 1408.67   469.4 1412.14   548.9 1420.78   558.9  1422.1   578.7 1425.13
#Mann= 3 , 0 , 0
       0      .1       0   125.4    .045       0   135.4      .1       0
Bank Sta=125.4,135.4
XS Rating Curve= 0 ,0
Exp/Cntr=0.3,0.1

Type RM Length L Ch R = 1 ,4204.5  ,290.8,292,293.2
XS GIS Cut Line= 3
     1708724.503      141345.499     1708894.711      141309.869
      1708991.41      141288.145
#Sta/Elev= 30
     9.7 1420.18    19.3 1413.23      29 1406.41    38.6 1399.76    48.3 1393.21
      58 1386.99    67.6 1381.39    77.3 1376.67    86.9 1372.66    96.6 1369.17
   106.3 1366.88   110.9 1366.61   115.9 1366.31   120.9  1366.8   125.6 1367.25
   135.3 1368.86   144.9 1370.32   154.6  1371.6   164.2 1373.12   173.9    1375
   183.8 1377.13   193.7 1379.36   203.6 1381.72   213.5 1384.18   223.5 1386.74
   233.4  1389.4   243.3 1392.15   253.2 1395.07   263.1 1398.18     273 1401.53
#Mann= 3 , 0 , 0
       0      .1       0   110.9    .045       0   120.9      .1       0
Bank Sta=110.9,120.9
XS Rating Curve= 0 ,0
Exp/Cntr=0.3,0.1

Type RM Length L Ch R = 1 ,3912.5  ,493,493.5,494
XS GIS Cut Line= 4
      1708677.42      141600.365     1708862.524      141610.045
     1708953.131      141596.509     1709055.295      141554.967
#Sta/Elev= 30
     9.8 1446.43    29.3 1438.07    48.8 1430.06    58.5 1426.17    68.3 1422.39
    87.8 1415.11   107.3  1408.1   126.8  1401.3   175.6 1384.68   194.5 1378.15
   203.7 1374.81   212.8 1370.87     222 1367.03   231.2 1364.51   235.3 1364.17
   240.3 1363.76   245.3 1364.09   249.5 1364.37   258.6 1366.16   267.8    1370
     277 1376.63     287 1384.58     297 1391.91     307 1398.77   327.1 1412.15
   337.1 1418.51   347.2 1424.73   357.2 1430.71   377.2 1442.25   387.3 1448.23
#Mann= 3 , 0 , 0
       0      .1       0   235.3    .045       0   245.3      .1       0
Bank Sta=235.3,245.3
XS Rating Curve= 0 ,0
Exp/Cntr=0.3,0.1

Type RM Length L Ch R = 1 ,3419    ,145.1,143.2,141.3
XS GIS Cut Line= 4
     1708654.284      142032.247     1708825.912      142086.485
     1708905.912       142076.26      1709041.31      142058.953
#Sta/Elev= 30
      10 1411.61      30 1402.29      40 1397.79      50 1393.61      60 1389.65
      70 1385.89      80 1382.38      90 1379.05     100 1376.04     150 1363.56
     160 1361.34     170 1359.41   190.1 1355.78   200.2 1354.19   230.4 1350.22
   240.5  1348.7   245.6 1348.16   250.6 1347.62   255.6 1348.08   260.6 1348.54
   270.4 1352.64   280.1 1358.03   289.9 1362.92   309.4 1371.72   328.9 1380.72
   348.4 1389.96   358.1  1394.7   377.6 1404.39   387.4 1409.43   397.1 1414.64
#Mann= 3 , 0 , 0
       0      .1       0   245.6    .045       0   255.6      .1       0
Bank Sta=245.6,255.6
XS Rating Curve= 0 ,0
Exp/Cntr=0.3,0.1

Type RM Length L Ch R = 1 ,3275.8  ,184.3,184.1,183.9
XS GIS Cut Line= 2
     1708823.952      142240.476      1709072.67      142184.563
#Sta/Elev= 28
     9.8 1363.81    19.6 1360.28    29.4 1356.89    39.2 1353.65      49 1350.65
    58.8    1348    68.6 1345.82    78.4 1344.27    88.2 1343.34      98 1342.65
   102.9 1342.53   107.9 1342.41   112.9 1343.44   117.7 1344.43   127.5 1350.23
   137.3 1358.52   147.1 1367.11   156.9 1375.46   166.7 1383.68   176.5 1391.69
   186.3 1399.29   196.1 1406.54   205.9  1413.3   215.7 1419.59   225.5 1425.33
   235.3 1430.18   245.1 1433.83   254.9 1435.76
#Mann= 3 , 0 , 0
       0      .1       0   102.9    .045       0   112.9      .1       0
Bank Sta=102.9,112.9
XS Rating Curve= 0 ,0
Exp/Cntr=0.3,0.1

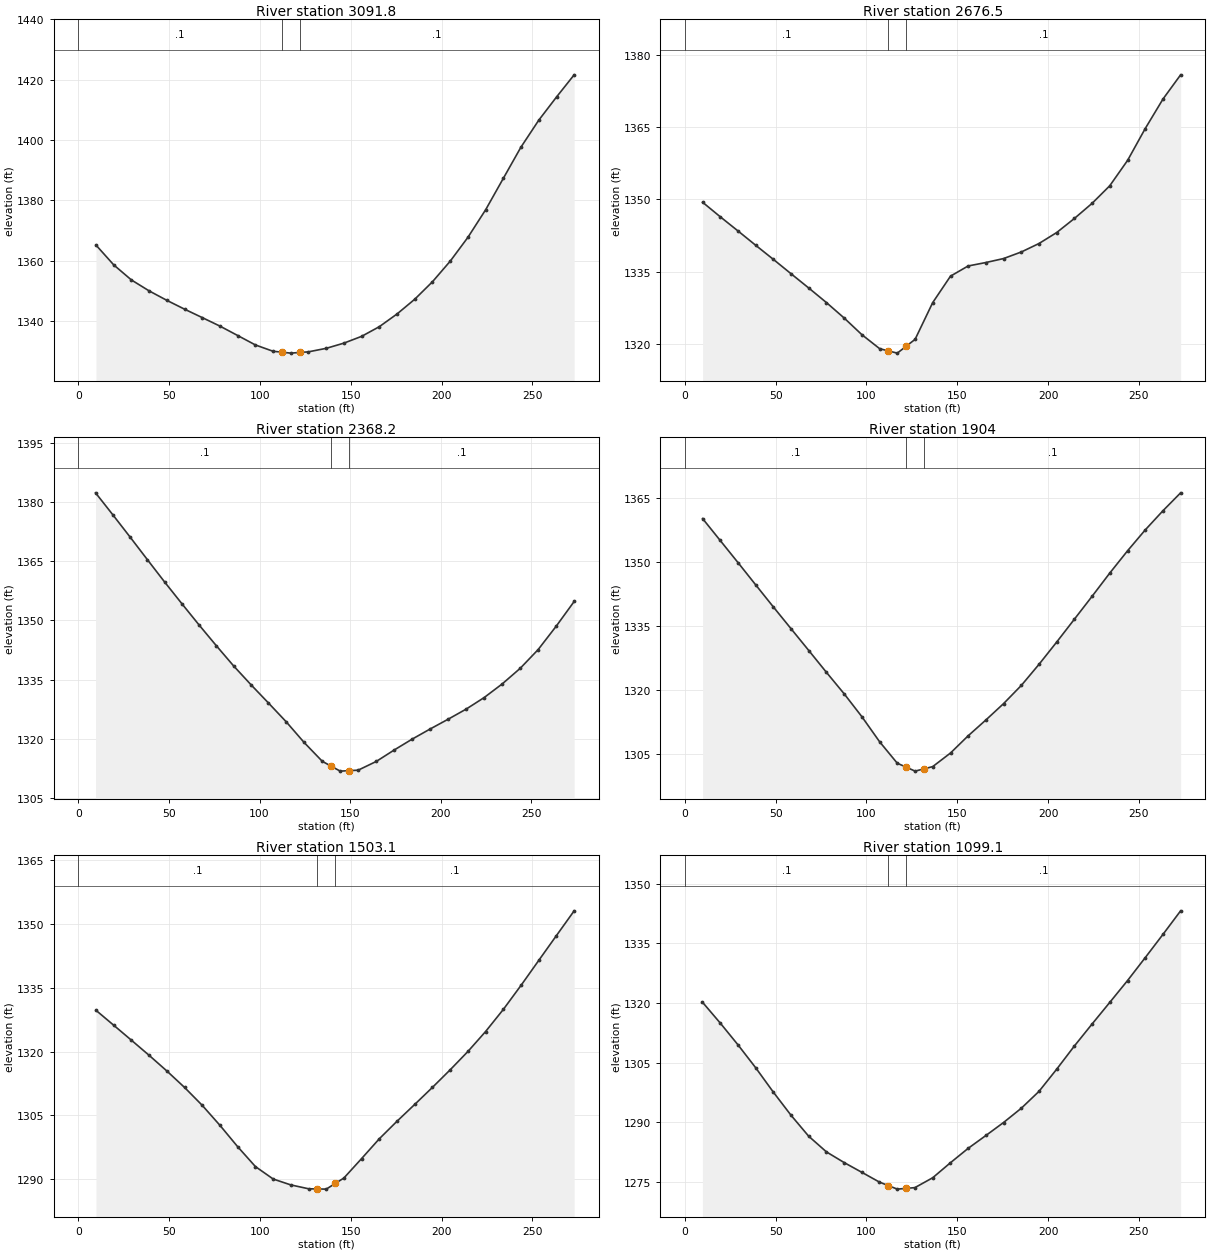
Type RM Length L Ch R = 1 ,3091.8  ,416.7,415.3,413.8
XS GIS Cut Line= 3
     1708874.041      142408.184     1709006.227      142374.139
     1709138.414      142340.094
#Sta/Elev= 30
     9.7 1365.22    19.5 1358.63    29.2 1353.65      39 1350.01    48.8 1346.86
    58.5 1343.95    68.3 1341.14      78 1338.33    87.8  1335.2    97.5 1332.09
   107.2    1330     112  1329.7     117 1329.38     122  1329.6   126.7 1329.81
   136.5 1330.97   146.2 1332.69     156 1334.95   165.7 1338.14   175.5 1342.37
   185.3 1347.29     195 1353.05   204.8  1359.9   214.5 1367.77   224.3 1376.95
     234 1387.33   243.7 1397.67   253.5  1406.6   263.3 1414.31     273 1421.65
#Mann= 3 , 0 , 0
       0      .1       0     112    .045       0     122      .1       0
Bank Sta=112,122
XS Rating Curve= 0 ,0
Exp/Cntr=0.3,0.1

Type RM Length L Ch R = 1 ,2676.5  ,300,308.3,316.6
XS GIS Cut Line= 3
     1709076.271      142777.663     1709205.213      142732.864
     1709334.401      142688.787
#Sta/Elev= 30
     9.8 1349.38    19.5 1346.37    29.3 1343.42      39 1340.46    48.8 1337.51
    58.5 1334.54    68.3 1331.56      78 1328.55    87.8 1325.33    97.5 1321.89
   107.3 1318.98     112 1318.53     117 1318.06     122 1319.52   126.8 1320.92
   136.5 1328.55   146.3 1334.04     156 1336.15   165.8 1336.87   175.5 1337.69
   185.3 1339.06     195 1340.81   204.8  1343.1   214.5 1346.01   224.3 1349.17
     234 1352.81   243.8 1358.07   253.5 1364.67   263.3 1370.81     273 1375.83
#Mann= 3 , 0 , 0
       0      .1       0     112    .045       0     122      .1       0
Bank Sta=112,122
XS Rating Curve= 0 ,0
Exp/Cntr=0.3,0.1

Type RM Length L Ch R = 1 ,2368.2  ,467.8,464.2,460.5
XS GIS Cut Line= 3
     1709129.983      143009.971     1709233.172      143028.175
     1709401.556      143040.022
#Sta/Elev= 30
     9.5 1382.44    19.1 1376.82    28.6 1371.18    38.1 1365.46    47.6 1359.79
    57.2 1354.23    66.7 1348.82    76.2 1343.56    85.7 1338.45    95.3 1333.66
   104.8 1329.09   114.7 1324.26   124.6    1319   134.6 1314.22   139.5 1312.98
   144.5 1311.72   149.5 1311.84   154.4 1311.96   164.4 1314.18   174.3 1317.09
   184.2 1319.85   194.1 1322.42   204.1 1324.92     214 1327.48   223.9  1330.4
   233.9 1333.88   243.8 1337.83   253.7 1342.59   263.7 1348.55   273.6 1354.83
#Mann= 3 , 0 , 0
       0      .1       0   139.5    .045       0   149.5      .1       0
Bank Sta=139.5,149.5
XS Rating Curve= 0 ,0
Exp/Cntr=0.3,0.1

Type RM Length L Ch R = 1 ,1904    ,402.9,400.9,398.9
XS GIS Cut Line= 3
     1709071.916      143502.011     1709207.581      143486.938
     1709343.246      143471.864
#Sta/Elev= 30
     9.8 1360.17    19.5 1355.03    29.3 1349.84      39 1344.64    48.7 1339.47
    58.5 1334.33    68.3  1329.2      78 1324.09    87.8 1319.03    97.5 1313.69
   107.3 1307.79     117 1302.77   121.8 1301.87   126.8 1300.92   131.8 1301.46
   136.5 1301.98   146.3 1305.17     156  1309.2   165.8 1312.93   175.5 1316.75
   185.3 1321.03     195 1325.96   204.8 1331.22   214.5 1336.56   224.3 1341.96
     234 1347.39   243.8 1352.62   253.5  1357.5   263.3 1362.02     273 1366.21
#Mann= 3 , 0 , 0
       0      .1       0   121.8    .045       0   131.8      .1       0
Bank Sta=121.8,131.8
XS Rating Curve= 0 ,0
Exp/Cntr=0.3,0.1

Type RM Length L Ch R = 1 ,1503.1  ,413.5,404,394.6
XS GIS Cut Line= 3
     1709151.363      143906.731     1709284.852      143878.219
     1709418.341      143849.706
#Sta/Elev= 30
     9.7 1329.71    19.5 1326.19    29.2 1322.69      39 1319.12    48.8 1315.43
    58.5 1311.58    68.2 1307.39      78 1302.67    87.7 1297.68    97.5    1293
   107.3 1290.07     117 1288.69   126.8 1287.78   131.5 1287.74   136.5  1287.7
   141.5 1289.04   146.2  1290.3     156 1294.89   165.7 1299.52   175.5 1303.66
   185.3 1307.63     195 1311.61   204.7 1315.71   214.5 1320.03   224.2  1324.7
     234 1329.91   243.8 1335.59   253.5 1341.42   263.2 1347.23     273 1353.07
#Mann= 3 , 0 , 0
       0      .1       0   131.5    .045       0   141.5      .1       0
Bank Sta=131.5,141.5
XS Rating Curve= 0 ,0
Exp/Cntr=0.3,0.1

Type RM Length L Ch R = 1 ,1099.1  ,380.3,391.5,402.6
XS GIS Cut Line= 3
     1709297.044      144342.405     1709402.862      144256.183
     1709509.531         144171.
#Sta/Elev= 30
     9.7 1320.21    19.5 1314.96    29.2 1309.52      39 1303.73    48.7 1297.61
    58.5 1291.76    68.2  1286.5      78 1282.55    87.7 1279.88    97.5 1277.41
   107.2 1274.95     112 1274.09     117 1273.19     122 1273.38   126.7 1273.57
   136.5 1276.05   146.2  1279.8     156 1283.44   165.8 1286.68   175.5 1289.94
   185.3 1293.54     195 1297.76   204.8 1303.37   214.5 1309.18   224.3 1314.74
     234 1320.15   243.8 1325.65   253.5 1331.39   263.3 1337.26     273 1343.17
#Mann= 3 , 0 , 0
       0      .1       0     112    .045       0     122      .1       0
Bank Sta=112,122
XS Rating Curve= 0 ,0
Exp/Cntr=0.3,0.1

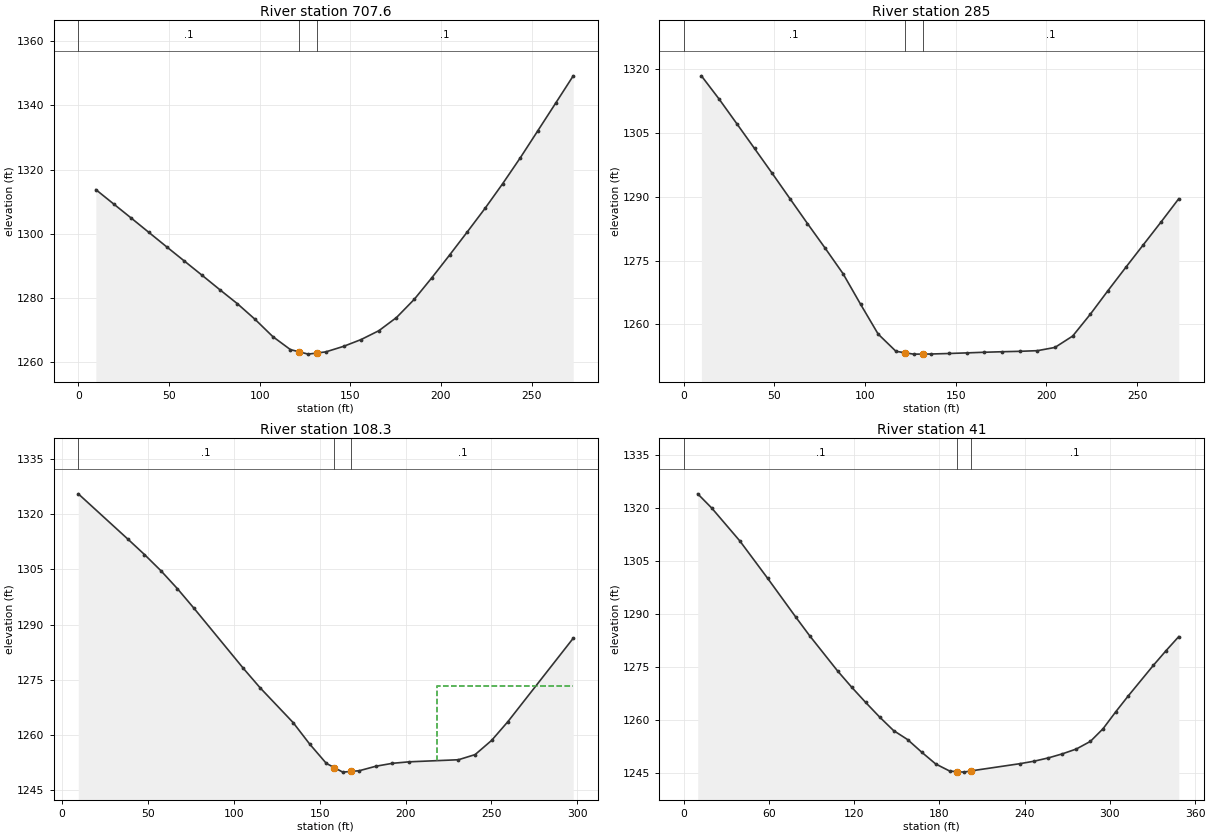
Type RM Length L Ch R = 1 ,707.6   ,433,422.5,416.6
XS GIS Cut Line= 3
     1709410.593      144635.956     1709545.766      144616.965
     1709680.938      144597.974
#Sta/Elev= 30
     9.7 1313.75    19.5 1309.29    29.3 1304.84      39 1300.39    48.7 1295.94
    58.5 1291.49    68.3 1287.04      78 1282.58    87.8 1278.16    97.5 1273.31
   107.3 1267.92     117 1263.87   121.8 1263.18   126.8 1262.46   131.8 1262.82
   136.5 1263.16   146.3 1264.88     156 1267.01   165.8 1269.77   175.5 1273.87
   185.3 1279.54     195 1286.27   204.8 1293.36   214.5 1300.53   224.3 1307.88
     234 1315.55   243.8 1323.69   253.5 1332.15   263.3 1340.72     273 1349.24
#Mann= 3 , 0 , 0
       0      .1       0   121.8    .045       0   131.8      .1       0
Bank Sta=121.8,131.8
XS Rating Curve= 0 ,0
Exp/Cntr=0.3,0.1

Type RM Length L Ch R = 1 ,285     ,176.1,176.7,177.4
XS GIS Cut Line= 3
       1709557.8      145067.399     1709681.772      145010.275
     1709805.744      144953.151
#Sta/Elev= 30
     9.7 1318.39    19.5 1312.92    29.2 1307.17      39 1301.33    48.8 1295.46
    58.5 1289.57    68.2  1283.7      78 1277.89    87.8 1271.94    97.5 1264.74
   107.2 1257.73     117 1253.69   121.8 1253.35   126.7 1253.02   131.8 1253.03
   136.5 1253.05   146.3 1253.17     156 1253.31   165.7 1253.46   175.5 1253.58
   185.2 1253.68     195 1253.83   204.7 1254.59   214.5 1257.27   224.2 1262.38
     234 1267.96   243.8 1273.41   253.5 1278.73   263.2 1284.04     273 1289.52
#Mann= 3 , 0 , 0
       0      .1       0   121.8    .045       0   131.8      .1       0
Bank Sta=121.8,131.8
XS Rating Curve= 0 ,0
Exp/Cntr=0.3,0.1

Type RM Length L Ch R = 1 ,108.3   ,71.5,67.3,63.1
XS GIS Cut Line= 4
     1709579.308      145188.088     1709694.416      145195.636
     1709818.537      145143.203     1709849.152      145106.945
#Sta/Elev= 23
     9.6 1325.56    38.5 1313.22    48.1 1309.05    57.7 1304.63    67.3 1299.74
    76.9 1294.44   105.7 1278.05   115.4 1272.79   134.6 1263.34   144.2 1257.51
   153.9 1252.24   158.5 1251.09   163.5 1249.85   168.5 1250.05   173.1 1250.23
   182.7 1251.45   192.4 1252.25     202 1252.65   230.8 1253.22   240.5 1254.62
   250.1 1258.48   259.6  1263.6   297.6 1286.28
#Mann= 3 , 0 , 0
     9.6      .1       0   158.5    .045       0   168.5      .1       0
#XS Ineff= 2 , 0
                          218.18         1273.28
Permanent Ineff=
       F       F
Bank Sta=158.5,168.5
XS Rating Curve= 0 ,0
Exp/Cntr=0.3,0.1

Type RM Length L Ch R = 1 ,41      ,35,41,47
XS GIS Cut Line= 4
     1709584.471      145216.027     1709722.711      145268.025
     1709836.853      145189.394     1709858.413      145131.054
#Sta/Elev= 30
     9.8 1324.03    19.7 1319.99    39.4 1310.72    59.1 1300.08    78.8 1289.16
    88.6 1283.86   108.3 1273.88   118.2 1269.29     128    1265   137.8 1260.87
   147.7 1257.01   157.6 1254.45   167.5 1250.89   177.4 1247.54   187.3 1245.53
   192.2 1245.39   197.2 1245.24   202.2 1245.59   236.8 1247.64   246.7 1248.34
   256.6 1249.26   266.5 1250.41   276.4 1251.79   286.3 1253.95   295.2 1257.53
   304.1  1262.3     313 1266.85   330.7 1275.51   339.6 1279.65   348.5 1283.61
#Mann= 3 , 0 , 0
       0      .1       0   192.2    .045       0   202.2      .1       0
Bank Sta=192.2,202.2
XS Rating Curve= 0 ,0
Exp/Cntr=0.3,0.1

Chan Stop Cuts=-1
Use User Specified Reach Order=0